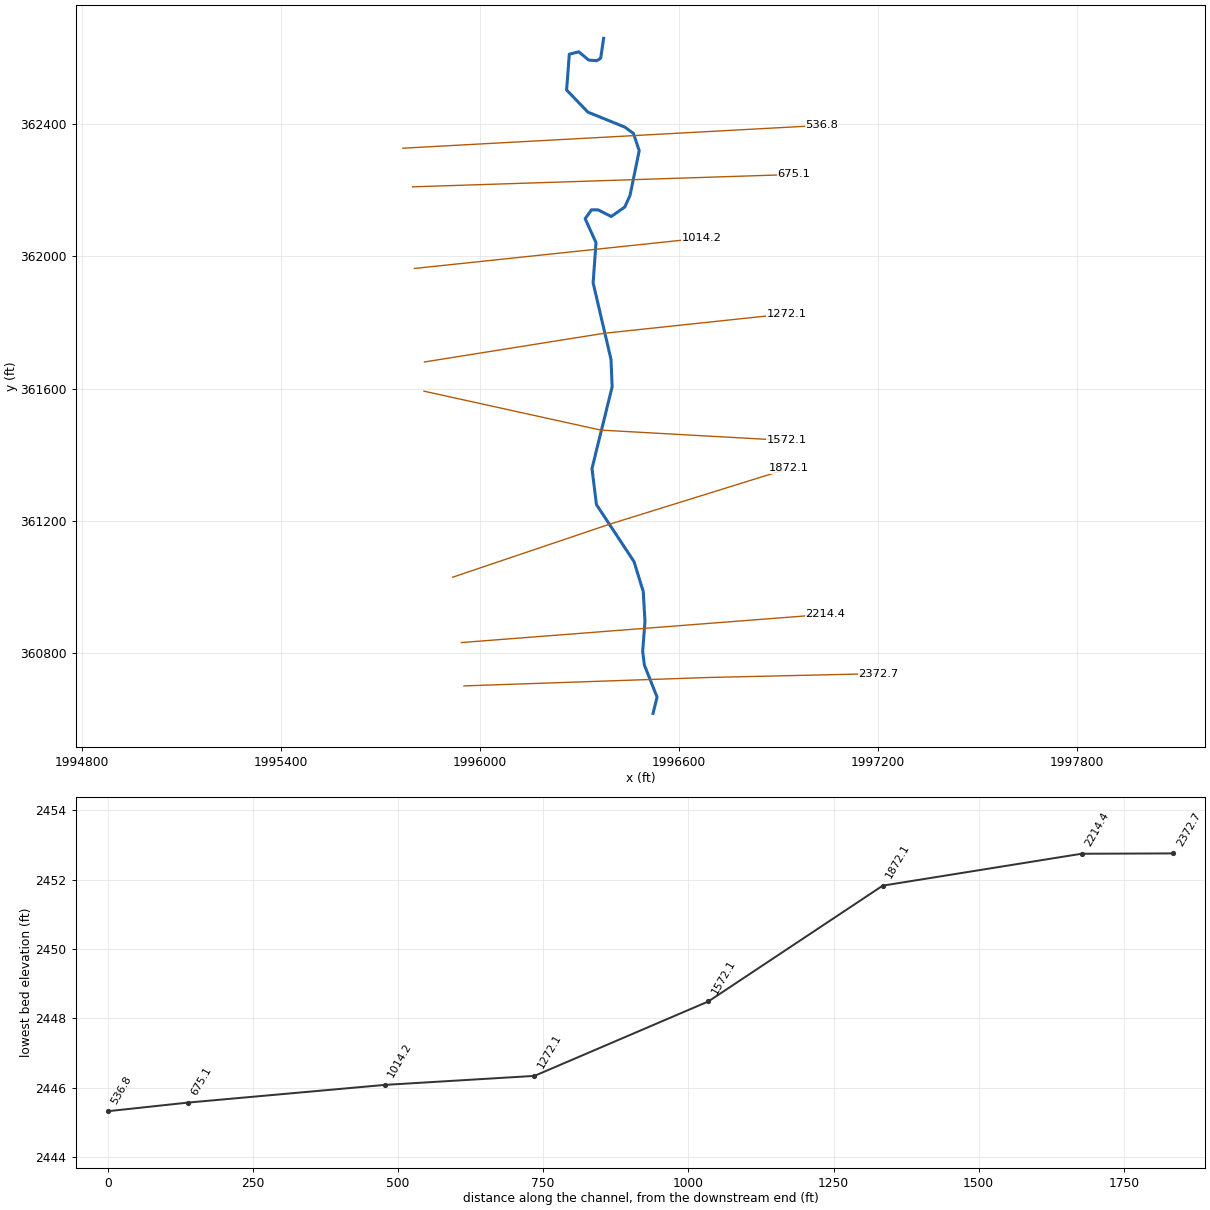
--- NP26.prj (project) ---

Proj Title=NP26
Current Plan=p01
Default Exp/Contr=0,0
English Units
Geom File=g01
Flow File=f01
Plan File=p01
BEGIN DESCRIPTION:
END DESCRIPTION:
DSS Export Rating Curves= 0
DSS Export Rating Curve Sorted= 0
DSS Export Volume Flow Curves= 0
DXF OffsetX= 0
DXF OffsetY= 0
DXF ScaleX= 0
DXF ScaleY= 0

--- NP26.p01 (plan) ---

Plan Title=Floodplain
Program Version=4.00
Geom File=g01
Flow File=f01
K Sum by GR=0
Std Step Tol=0.01
Critical Tol=0.01
Num of Std Step Trials=20
Max Error Tol=0.3
Flow Tol Ratio=0.001
Split Flow NTrial=30
Split Flow Tol=0.02
Split Flow Ratio=0.02
Log Output Level=0
Friction Slope Method=1
Unsteady Friction Slope Method=2
Unsteady Bridges Friction Slope Method=1
Global Log Level=0
CheckData=False
Run HTab=0
Run UNet=0
Run PostProcess=0
UNET Theta=0
UNET Theta Warmup=0
UNET ZTol=0
UNET ZSATol=0
UNET MxIter=0
UNET MaxInSteps=0
UNET DtIC=0
UNET DtMin=0
UNET MaxCRTS=0
UNET WFStab=0
UNET SFStab=0
UNET WFX=0
UNET SFX=0
UNET DSS MLevel=0
UNET DZMax Abort=0
UNET Convert EG Bridges=0
UNET Use Existing IB Tables=0
UNET Froude Limit=0
UNET Froude Power=0
Write IC File=0
Echo Input=False
Echo Output=False
Write Detailed=0

--- NP26.f01 (steady flow) ---

Flow Title=NFF Regression Equation
Program Version=4.00
Number of Profiles=1
Profile Names=P100yr
River Rch & RM=NP26,Main      ,2372.7
545.4800
Boundary for River Rch & Prof#=NP26,Main      ,1
Up Type=0
Dn Type=3
Dn Slope=0.001289

--- NP26.g01 (geometry) ---

Geom Title=USGS 3m DEM
Program Version=4.00

River Reach=NP26     ,Main
Reach XY= 30
     1996521.113      360619.103     1996533.265      360668.263
     1996495.071      360764.937     1996489.862      360806.603
     1996496.807      360896.881     1996491.598      360987.159
     1996463.821      361077.437     1996350.592      361249.652
     1996337.085      361358.687     1996397.849      361605.215
     1996394.376      361688.548     1996340.557      361919.450
     1996349.238      362040.977     1996316.538      362113.110
     1996335.348      362139.937     1996355.639      362139.937
     1996395.228      362119.909     1996436.043      362148.617
     1996451.668      362183.339     1996479.446      362318.756
     1996462.085      362370.839     1996436.043      362389.937
     1996324.932      362435.075     1996260.622      362501.946
     1996268.774      362610.145     1996297.154      362617.367
     1996327.288      362592.442     1996351.842      362590.458
     1996363.392      362598.333     1996372.170      362658.045

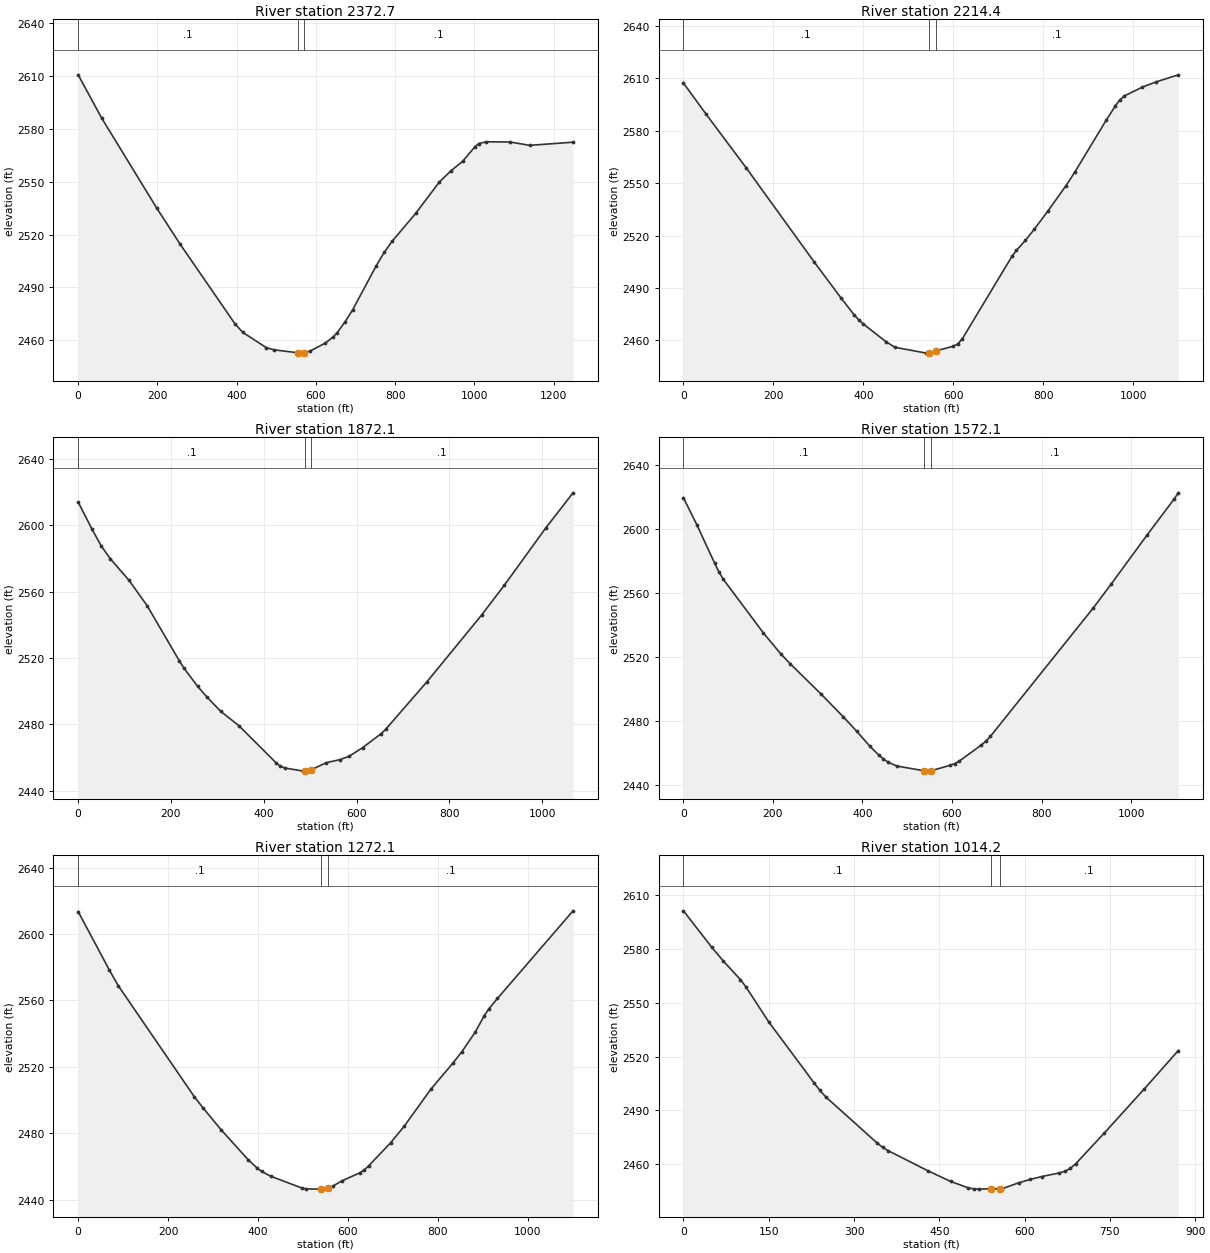
Type RM Length L Ch R = 1 ,2372.7,156.9,158.3,160
XS GIS Cut Line= 3
     1995951.209      360702.078     1996693.381      360727.683
     1997199.780      360739.160
#Sta/Elev= 30
       0 2610.56    59.4 2586.02   198.0 2535.11   257.4 2514.55   396.1 2469.28
   415.9 2464.47   475.3 2455.82   495.1 2454.62   554.2 2452.96   564.4 2452.76
   569.2 2452.88   584.2 2453.80   623.8 2458.45   643.6 2461.93   653.5 2464.31
   673.3 2470.38   693.1 2477.41   752.6 2502.40   772.4 2509.82   792.3 2516.14
   851.9 2531.98   911.5 2549.76   941.2 2556.18   971.0 2561.65  1000.8 2569.60
  1010.8 2571.54  1030.6 2572.61  1090.2 2572.46  1139.9 2570.58  1249.1 2572.36
#Mann= 3 , 0 , 0
       0     0.1       0   554.2   0.045       0   569.2     0.1       0
Bank Sta=   554.2,   569.2
Exp/Cntr=0.3,0.1

Type RM Length L Ch R = 1 ,2214.4,336.9,342.3,347.1
XS GIS Cut Line= 2
     1995943.593      360833.053     1997040.386      360918.138
#Sta/Elev= 30
       0 2607.35    50.0 2589.66   140.0 2558.63   290.0 2505.16   350.0 2484.42
   380.0 2474.51   390.0 2471.69   400.0 2469.41   450.0 2459.32   470.0 2456.10
   540.0 2452.75   545.6 2452.94   560.6 2453.96   600.0 2456.72   610.0 2458.08
   620.0 2460.98   730.1 2508.08   740.1 2511.54   760.1 2517.27   780.1 2523.73
   810.1 2534.06   850.1 2548.49   870.1 2556.40   940.1 2586.22   960.1 2594.26
   970.1 2597.72   980.1 2599.96  1020.1 2605.01  1050.1 2607.95  1100.1 2612.05
#Mann= 3 , 0 , 0
       0     0.1       0   545.6   0.045       0   560.6     0.1       0
Bank Sta=   545.6,   560.6
Exp/Cntr=0.3,0.1

Type RM Length L Ch R = 1 ,1872.1,312.1,300.1,292.4
XS GIS Cut Line= 3
     1995917.285      361030.375     1996386.319      361189.236
     1996931.521      361359.216
#Sta/Elev= 30
       0 2613.93    29.7 2597.67    49.5 2587.60    69.3 2579.75   109.0 2567.00
   148.6 2551.52   217.9 2518.33   227.8 2513.94   257.5 2502.88   277.3 2496.53
   307.0 2487.88   346.6 2479.14   425.9 2457.00   435.8 2454.78   445.7 2453.70
   485.3 2451.83   487.7 2451.85   495.2 2451.93   502.7 2452.73   534.6 2456.90
   564.1 2458.77   583.8 2460.76   613.4 2466.06   652.8 2474.40   662.6 2477.04
   751.2 2505.55   869.4 2545.89   918.6 2563.96  1007.2 2598.19  1066.3 2619.49
#Mann= 3 , 0 , 0
       0     0.1       0   487.7   0.045       0   502.7     0.1       0
Bank Sta=   487.7,   502.7
Exp/Cntr=0.3,0.1

Type RM Length L Ch R = 1 ,1572.1,291.4,299.7,303.3
XS GIS Cut Line= 3
     1995830.877      361592.294     1996363.923      361474.716
     1996922.886      361443.493
#Sta/Elev= 30
       0 2619.62    29.8 2602.82    69.5 2578.80    79.4 2573.16    89.3 2568.52
   178.6 2535.01   218.3 2521.62   238.2 2515.80   307.7 2496.68   357.3 2482.43
   387.1 2473.49   416.8 2463.97   436.7 2458.51   446.6 2456.18   456.5 2454.22
   476.4 2451.70   538.4 2448.68   545.9 2448.49   553.4 2448.74   595.8 2452.13
   605.8 2453.16   615.8 2454.66   665.8 2464.89   675.8 2467.28   685.8 2470.24
   915.8 2550.71   955.7 2565.60  1035.7 2596.25  1095.7 2618.62  1105.7 2622.73
#Mann= 3 , 0 , 0
       0     0.1       0   538.4   0.045       0   553.4     0.1       0
Bank Sta=   538.4,   553.4
Exp/Cntr=0.3,0.1

Type RM Length L Ch R = 1 ,1272.1,258.8,257.7,257.8
XS GIS Cut Line= 3
     1995832.360      361680.580     1996372.673      361767.014
     1996922.844      361825.711
#Sta/Elev= 30
       0 2613.56    69.6 2578.22    89.5 2568.77   258.7 2501.88   278.6 2494.97
   318.4 2481.95   378.0 2464.08   398.0 2459.04   407.9 2457.03   427.8 2454.16
   497.4 2447.03   507.4 2446.48   537.2 2446.34   539.7 2446.36   554.7 2446.82
   566.9 2448.26   586.7 2451.35   626.2 2456.13   636.1 2457.90   646.0 2460.36
   695.4 2474.43   725.0 2484.20   784.3 2506.56   833.7 2522.36   853.5 2529.21
   883.1 2540.98   902.9 2550.69   912.8 2554.80   932.5 2561.25  1100.5 2614.01
#Mann= 3 , 0 , 0
       0     0.1       0   539.7   0.045       0   554.7     0.1       0
Bank Sta=   539.7,   554.7
Exp/Cntr=0.3,0.1

Type RM Length L Ch R = 1 ,1014.2,340.8,338.7,336.5
XS GIS Cut Line= 2
     1995802.059      361962.928     1996667.559      362054.650
#Sta/Elev= 30
       0 2601.44    50.0 2581.01    70.0 2573.48   100.0 2563.10   110.0 2558.95
   150.1 2539.39   230.1 2505.25   240.1 2501.16   250.1 2497.64   340.1 2471.98
   350.1 2469.46   360.1 2467.53   430.2 2456.29   470.2 2450.35   500.2 2446.88
   510.2 2446.21   520.2 2446.08   541.3 2446.26   556.3 2446.22   560.2 2446.27
   590.2 2449.68   610.2 2451.53   630.2 2453.11   660.3 2455.06   670.3 2455.96
   680.3 2457.63   690.3 2460.38   740.3 2477.42   810.3 2501.94   870.4 2523.46
#Mann= 3 , 0 , 0
       0     0.1       0   541.3   0.045       0   556.3     0.1       0
Bank Sta=   541.3,   556.3
Exp/Cntr=0.3,0.1

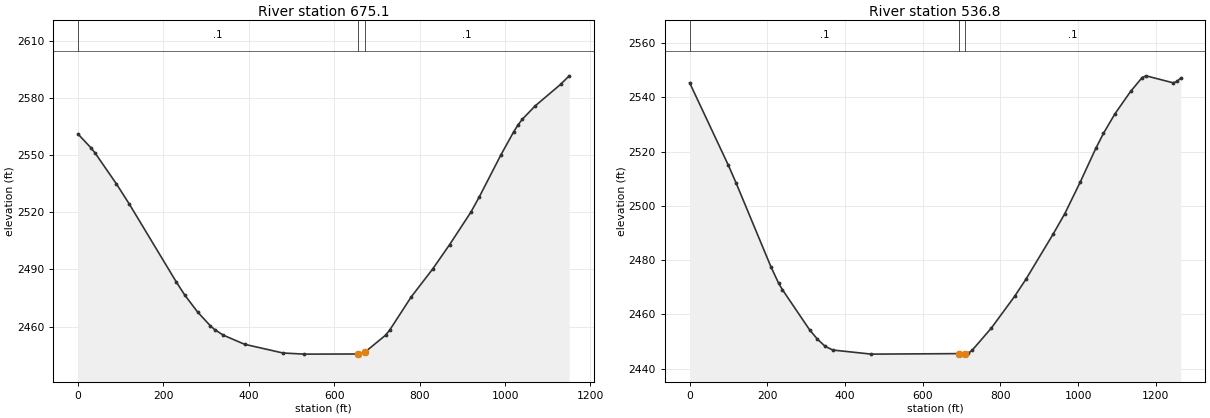
Type RM Length L Ch R = 1 ,675.1,143.5,138.6,137
XS GIS Cut Line= 2
     1995796.177      362209.506     1996945.864      362246.881
#Sta/Elev= 30
       0 2561.03    30.0 2553.86    40.0 2551.09    90.0 2534.86   120.0 2524.35
   230.1 2483.47   250.1 2476.53   280.1 2467.68   310.1 2460.40   320.1 2458.46
   340.1 2455.54   390.1 2450.74   480.1 2446.16   530.1 2445.57   656.3 2445.65
   671.3 2446.49   720.2 2455.50   730.2 2458.27   780.2 2475.54   830.2 2490.11
   870.2 2502.99   920.2 2520.10   940.2 2528.23   990.2 2550.01  1020.3 2562.18
  1030.3 2565.75  1040.3 2568.71  1070.3 2575.69  1130.3 2587.10  1150.3 2591.53
#Mann= 3 , 0 , 0
       0     0.1       0   656.3   0.045       0   671.3     0.1       0
Bank Sta=   656.3,   671.3
Exp/Cntr=0.3,0.1

Type RM Length L Ch R = 1 ,536.8,530.9,535.4,529.7
XS GIS Cut Line= 2
     1995767.135      362326.260     1997029.546      362395.118
#Sta/Elev= 30
       0 2545.37    99.6 2514.99   119.5 2508.46   209.1 2477.59   229.0 2471.47
   238.9 2469.07   308.6 2454.33   328.5 2450.91   348.4 2448.25   368.3 2446.83
   467.9 2445.32   694.3 2445.51   709.3 2445.50   716.8 2445.63   726.7 2446.66
   776.5 2454.92   836.2 2466.58   866.1 2473.05   935.8 2489.63   965.6 2497.11
  1005.5 2508.81  1045.3 2521.15  1065.2 2526.74  1095.0 2534.00  1134.9 2542.16
  1164.7 2547.30  1174.7 2547.93  1244.4 2545.36  1254.3 2545.85  1264.3 2547.15
#Mann= 3 , 0 , 0
       0     0.1       0   694.3   0.045       0   709.3     0.1       0
Bank Sta=   694.3,   709.3
Exp/Cntr=0.3,0.1